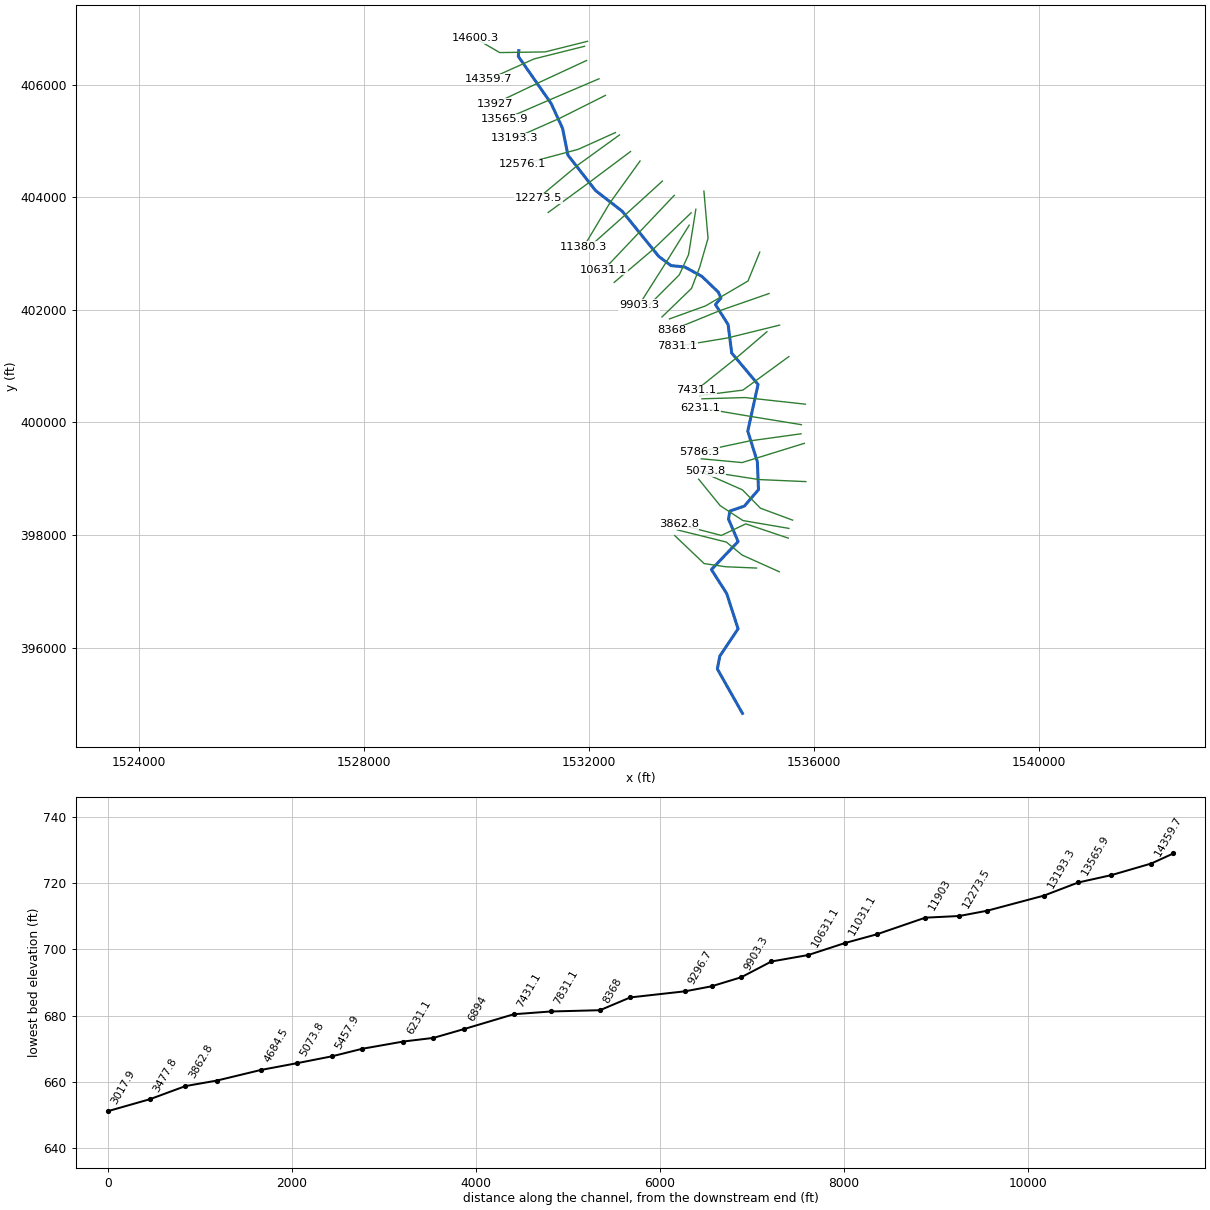
--- LFMILLCR.prj (project) ---

Proj Title=LFMILLCR
Current Plan=p01
Default Exp/Contr=0,0
English Units
Geom File=g01
Flow File=f01
Plan File=p01
BEGIN DESCRIPTION:
END DESCRIPTION:
DSS Export Rating Curves= 0
DSS Export Rating Curve Sorted= 0
DSS Export Volume Flow Curves= 0
DXF OffsetX= 0
DXF OffsetY= 0
DXF ScaleX= 0
DXF ScaleY= 0

--- LFMILLCR.p01 (plan) ---

Plan Title=Floodplain
Program Version=4.00
Geom File=g01
Flow File=f01
K Sum by GR=0
Std Step Tol=0.01
Critical Tol=0.01
Num of Std Step Trials=20
Max Error Tol=0.3
Flow Tol Ratio=0.001
Split Flow NTrial=30
Split Flow Tol=0.02
Split Flow Ratio=0.02
Log Output Level=0
Friction Slope Method=1
Unsteady Friction Slope Method=2
Unsteady Bridges Friction Slope Method=1
Global Log Level=0
CheckData=False
Run HTab=0
Run UNet=0
Run PostProcess=0
UNET Theta=0
UNET Theta Warmup=0
UNET ZTol=0
UNET ZSATol=0
UNET MxIter=0
UNET MaxInSteps=0
UNET DtIC=0
UNET DtMin=0
UNET MaxCRTS=0
UNET WFStab=0
UNET SFStab=0
UNET WFX=0
UNET SFX=0
UNET DSS MLevel=0
UNET DZMax Abort=0
UNET Convert EG Bridges=0
UNET Use Existing IB Tables=0
UNET Froude Limit=0
UNET Froude Power=0
Write IC File=0
Echo Input=False
Echo Output=False
Write Detailed=0

--- LFMILLCR.f01 (steady flow) ---

Flow Title=NFF Regression Equation
Program Version=4.00
Number of Profiles=1
Profile Names=P100yr
River Rch & RM=LFMILLCR,Main      ,14600.3
     376
River Rch & RM=LFMILLCR,Main      ,14359.7
     379
River Rch & RM=LFMILLCR,Main      ,12576.1
     420
River Rch & RM=LFMILLCR,Main      ,12273.5
     455
River Rch & RM=LFMILLCR,Main      ,11380.3
     484
River Rch & RM=LFMILLCR,Main      ,9580.9
     517
River Rch & RM=LFMILLCR,Main      ,9296.7
     800
River Rch & RM=LFMILLCR,Main      ,8697.6
     802
River Rch & RM=LFMILLCR,Main      ,8368
     908
River Rch & RM=LFMILLCR,Main      ,6894
     925
River Rch & RM=LFMILLCR,Main      ,6558.9
    1050
River Rch & RM=LFMILLCR,Main      ,5073.8
    1097
River Rch & RM=LFMILLCR,Main      ,3862.8
    1201
River Rch & RM=LFMILLCR,Main      ,287.4
    1286
Boundary for River Rch & Prof#=LFMILLCR,Main      ,1
Up Type=0
Dn Type=3
Dn Slope=0.00282

--- LFMILLCR.g01 (geometry) ---

Geom Title=USGS 10m DEM
Program Version=4.00

River Reach=LFMILLCR        ,Main
Reach XY= 30
      1530754.52      406606.263     1530744.893      406504.708
     1531328.431      405667.635     1531531.996       405225.15
     1531627.848      404747.801     1532119.226      404118.124
     1532591.925      403752.139     1533241.502      402948.464
     1533459.143      402785.872     1533701.821      402761.951
     1534006.724      402595.132     1534300.021       402313.79
     1534346.242      402210.043     1534248.528      402093.743
     1534473.559      401738.116     1534537.328      401233.095
      1535005.67      400674.058     1534822.775      399844.651
     1534993.133      399300.169     1535013.603      398805.012
     1534762.318      398512.568     1534504.314      398424.394
     1534480.764      398281.916     1534650.977      397882.555
     1534176.431      397384.648     1534447.413      396961.971
     1534650.523      396332.642     1534325.746      395846.582
     1534282.596      395617.913     1534728.436      394829.503

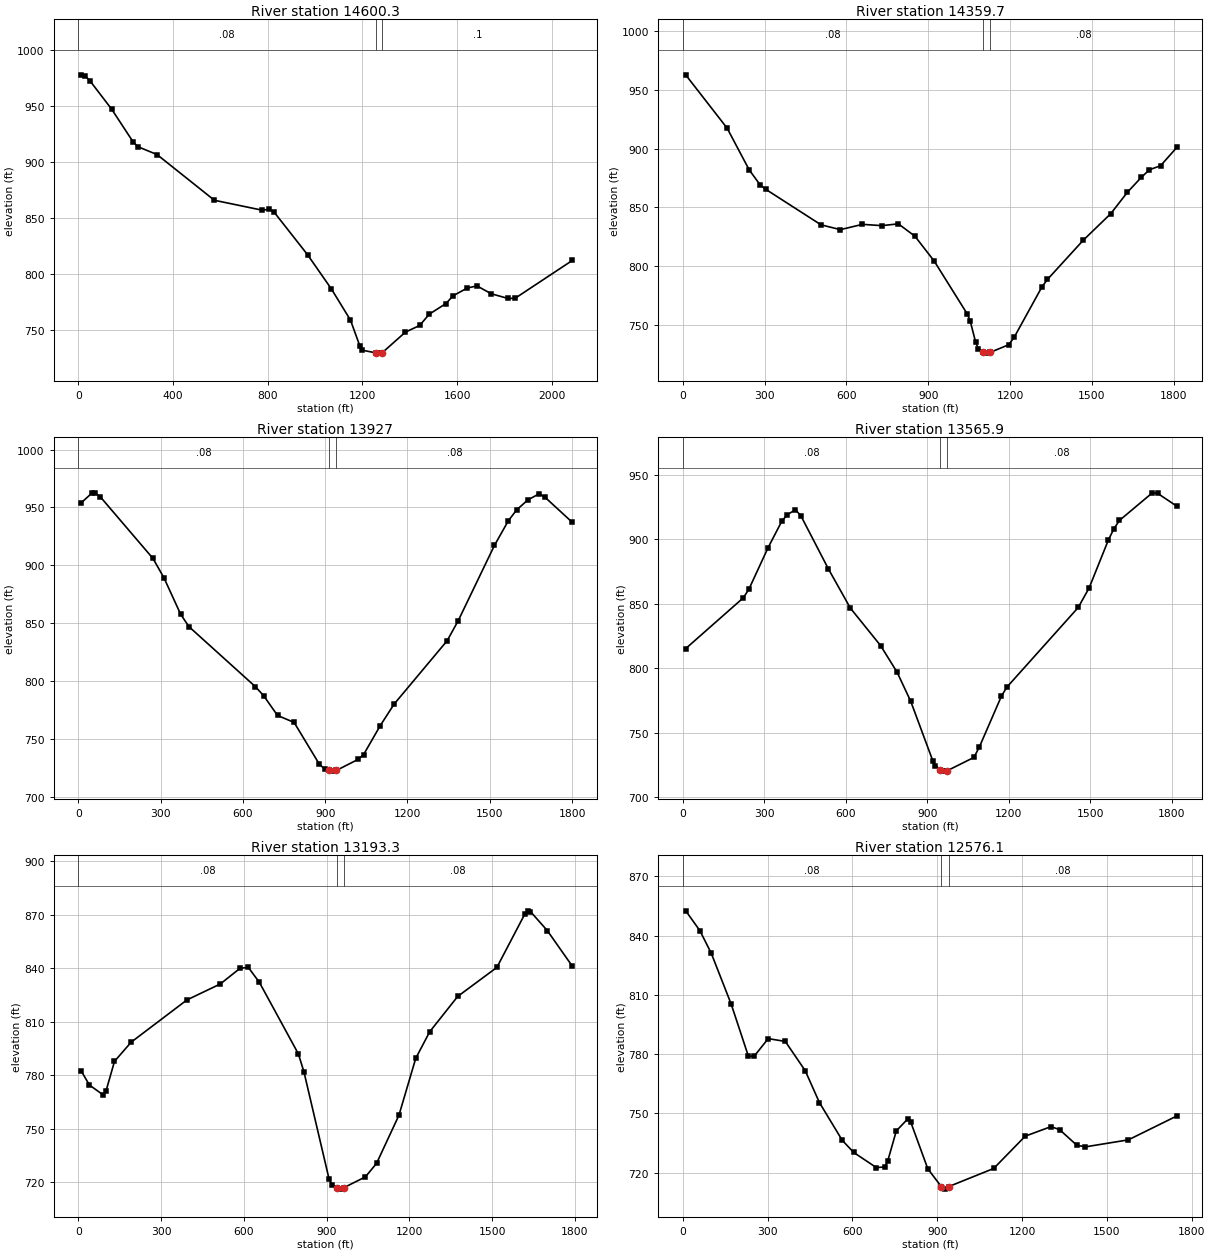
Type RM Length L Ch R = 1 ,14600.3 ,230.6,240.5,251.1
XS GIS Cut Line= 4
     1531975.362      406771.149      1531221.92      406582.789
     1530415.501      406571.016     1529979.918      406824.126
#Sta/Elev= 30
    10.1  977.63    30.3  976.46    50.4     972   141.2  946.92     232  917.59
   252.2  913.39   332.8  906.38   574.9  865.56   776.6   856.7   806.9  857.45
     827  854.98   968.2  816.97    1069  786.34  1149.6   758.5    1190  734.93
    1200  731.58  1258.1  729.17  1270.6  728.99  1283.1  729.25  1381.5  747.74
    1442  753.72  1482.3   763.8  1552.9  773.29  1583.1  780.27  1643.6  787.21
  1683.9  789.02  1744.3  782.01  1814.9  777.83  1845.1  778.03  2086.9  811.86
#Mann= 3 , 0 , 0
       0     .08       0  1258.1    .045       0  1283.1      .1       0
Bank Sta=1258.1,1283.1
XS Rating Curve= 0 ,0
Exp/Cntr=0.3,0.1

Type RM Length L Ch R = 1 ,14359.7 ,432.2,432.8,433.6
XS GIS Cut Line= 3
     1531922.386      406682.855     1531027.673      406459.177
     1530215.368      406094.229
#Sta/Elev= 30
    10.1  962.88   162.2  917.49   243.2  881.97   283.8  869.05     304  865.41
   506.7  835.17   577.7  831.07   658.7  835.58   729.7  834.48   790.5  836.01
   851.3  825.45   922.2  804.21  1043.7  759.07  1053.8  753.42    1074  735.16
  1084.2  729.42    1102  726.48  1114.5  725.94    1127  726.55  1195.5  733.11
  1215.7   739.6  1316.9  782.23  1337.2  788.66  1468.7  822.06  1569.9  844.75
  1630.6  862.89  1681.2  875.48  1711.6   882.1  1752.1  885.46  1812.8  901.28
#Mann= 3 , 0 , 0
       0     .08       0    1102    .045       0    1127     .08       0
Bank Sta=1102,1127
XS Rating Curve= 0 ,0
Exp/Cntr=0.3,0.1

Type RM Length L Ch R = 1 ,13927   ,362,361.1,360.1
XS GIS Cut Line= 3
     1531957.703      406429.746     1531133.859      406048.288
     1530327.207      405664.531
#Sta/Elev= 30
    10.1  953.83    50.4  962.52    60.5  962.61    80.7  959.08   272.4  905.96
   312.7  889.13   373.2  857.83   403.5  847.12   645.6  795.34   675.9  787.51
   726.3  770.49   786.8  764.46   877.6  728.87   897.8  724.14   915.7     723
   928.2  722.44   940.7  723.02  1019.5  732.52  1039.8  736.59  1100.7  761.69
  1151.5  780.35  1344.4  834.91    1385  852.29  1516.9  917.19  1567.7   938.5
  1598.1  947.95  1638.7  956.46  1679.3   961.7  1699.6  959.15  1801.2  937.05
#Mann= 3 , 0 , 0
       0     .08       0   915.7    .045       0   940.7     .08       0
Bank Sta=915.7,940.7
XS Rating Curve= 0 ,0
Exp/Cntr=0.3,0.1

Type RM Length L Ch R = 1 ,13565.9 ,372.3,372.6,372.8
XS GIS Cut Line= 3
      1532179.49      406105.503     1531342.556      405748.237
     1530506.975      405387.795
#Sta/Elev= 30
    10.1  815.14   222.4  854.53   242.7  861.06   313.4  893.27     364  913.83
   384.2  918.95   414.6  922.84   434.8  918.04   535.9  876.95   616.8  846.57
     728  817.55   788.7  796.98   839.2  774.29   920.1  728.39   930.2  724.47
   948.1  721.45   960.6  720.21   973.1  720.49  1071.8  730.84    1092  738.97
  1172.9  778.22  1193.1  785.28    1456  847.06  1496.4  862.34  1567.2  899.46
  1587.4  908.09  1607.7  914.53    1729  935.94  1749.2  935.42    1820  925.45
#Mann= 3 , 0 , 0
       0     .08       0   948.1    .045       0   973.1     .08       0
Bank Sta=948.1,973.1
XS Rating Curve= 0 ,0
Exp/Cntr=0.3,0.1

Type RM Length L Ch R = 1 ,13193.3 ,621.5,617.3,613
XS GIS Cut Line= 3
     1532293.558      405810.367     1531481.228      405403.159
     1530674.497      405046.473
#Sta/Elev= 30
    10.1   782.6    40.4  774.56    90.9  768.94     101  771.39   131.3   787.8
   191.8  798.55   393.8  822.19   514.9  831.14   585.6  839.83   615.9  840.49
   656.3  832.06   797.6     792   817.8  781.94   908.7  722.02   918.8  718.78
   936.7  716.65   949.2  716.25   961.7  717.01  1040.5   723.1    1081  730.68
  1162.1  757.63    1223  789.51  1273.7  804.41  1375.1  824.17    1517  840.41
  1618.4  870.34  1628.5  872.09  1638.7  871.67  1699.5  861.06  1790.7  841.01
#Mann= 3 , 0 , 0
       0     .08       0   936.7    .045       0   961.7     .08       0
Bank Sta=936.7,961.7
XS Rating Curve= 0 ,0
Exp/Cntr=0.3,0.1

Type RM Length L Ch R = 1 ,12576.1 ,292.3,302.5,314.7
XS GIS Cut Line= 3
     1532471.347       405149.72     1531810.547      404852.226
     1530821.654      404587.344
#Sta/Elev= 30
    10.1  852.56    60.4  842.46   100.6  830.99   171.1  805.24   231.5  779.09
   251.6  778.86   301.9  787.87   362.3  786.45   432.8  771.64   483.1  755.49
   563.6  736.43   603.9  730.29   684.4  722.59   714.6   722.9   724.7  725.92
   755.1  741.16   795.6  747.23   805.8  745.76   866.6  721.94   914.9  712.86
   927.4  711.68   939.9  712.93  1099.7  722.14  1211.2  738.49  1302.4  743.32
  1332.8  741.79  1393.7   733.9  1424.1  733.08  1576.1  736.62  1748.4  748.77
#Mann= 3 , 0 , 0
       0     .08       0   914.9    .045       0   939.9     .08       0
Bank Sta=914.9,939.9
XS Rating Curve= 0 ,0
Exp/Cntr=0.3,0.1

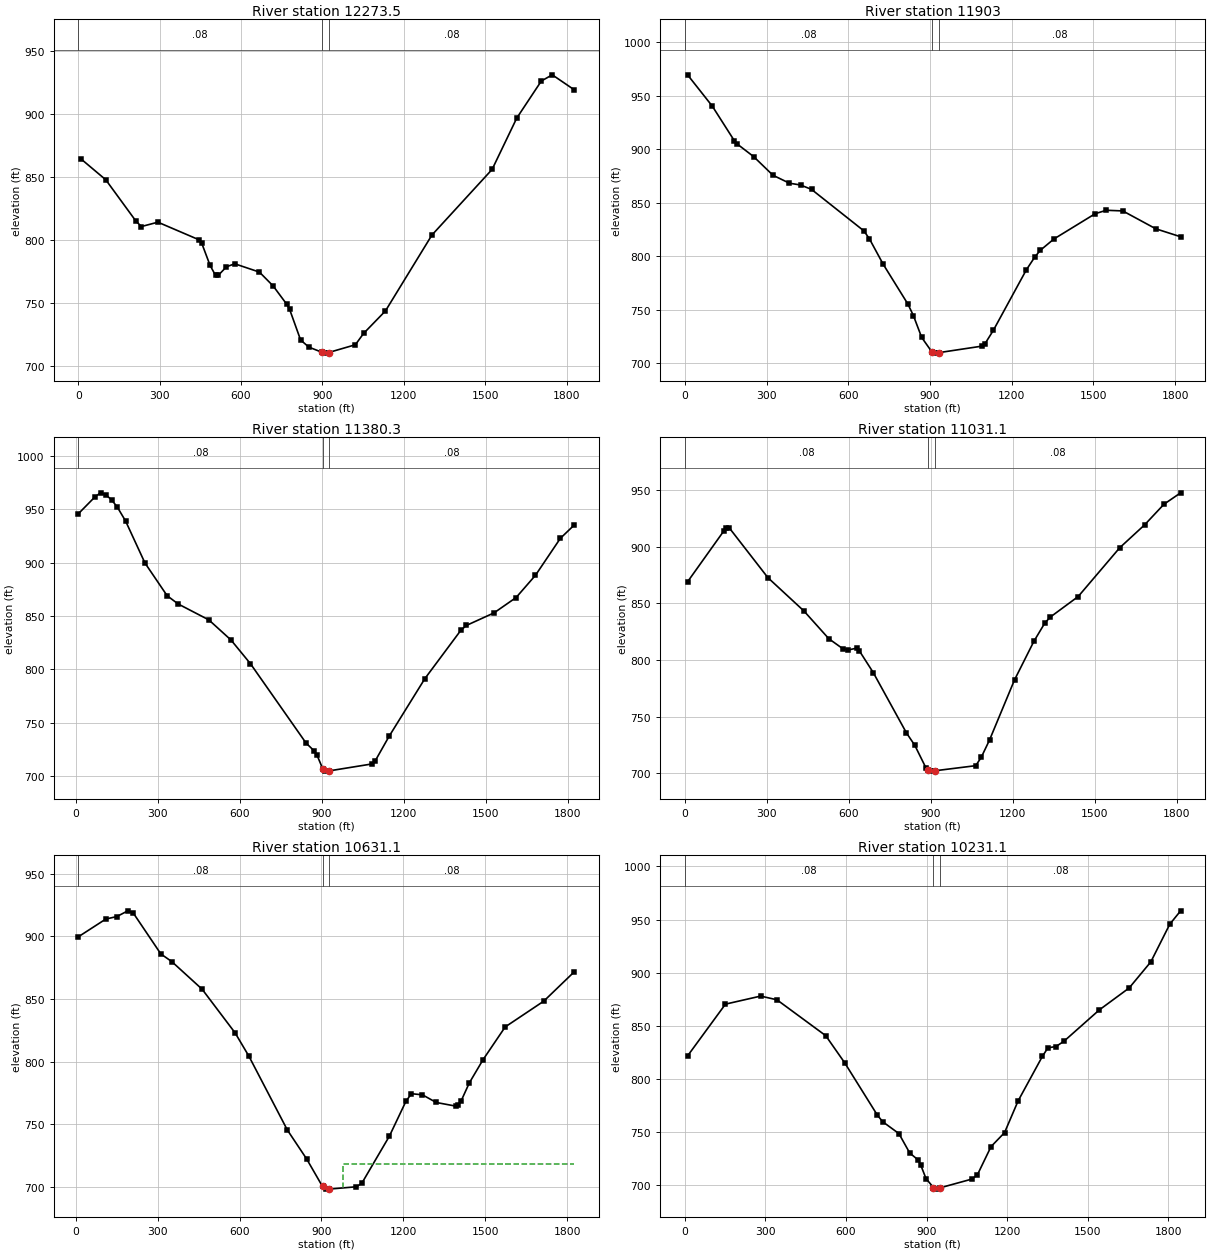
Type RM Length L Ch R = 1 ,12273.5 ,370.1,370.5,368.8
XS GIS Cut Line= 3
       1532543.3      405107.238     1531805.334      404573.887
     1531100.995      403985.657
#Sta/Elev= 30
    10.1  864.39   101.2  847.87   212.5  814.99   232.7  810.71   293.4  814.17
   445.1  800.16   455.3  797.29   485.6   779.9   505.8   771.9     516  771.91
   546.3  778.73   576.7   781.1   667.7   774.5   718.3  763.49   768.9   748.8
     779  744.91   819.5  720.56   849.8  714.89     898  710.79   910.5  710.09
     923  710.58  1021.5  716.75  1051.7  725.73  1132.4  743.64  1303.8  803.96
  1525.7  856.12  1616.4  896.85  1707.2  926.39  1747.5  931.29  1828.2  919.44
#Mann= 3 , 0 , 0
       0     .08       0     898    .045       0     923     .08       0
Bank Sta=898,923
XS Rating Curve= 0 ,0
Exp/Cntr=0.3,0.1

Type RM Length L Ch R = 1 ,11903   ,514.3,522.7,533.6
XS GIS Cut Line= 3
     1532739.667       404812.78     1532010.946      404267.643
     1531276.631      403730.185
#Sta/Elev= 30
    10.1   969.4   101.1   940.1     182  907.82   192.1  904.86   252.8  893.02
   323.6  875.65   384.2  868.21   424.7  866.56   465.1  862.45   657.3  823.73
   677.5  816.38     728  792.65   819.1   755.3   839.3   744.5   869.6  724.18
   907.7  710.47   920.2  709.58   932.7  710.04  1092.1  716.16  1102.2  718.48
  1132.5  730.82  1253.8  787.39  1284.2  799.09  1304.4  805.46  1354.9  816.14
  1506.6  839.77  1547.1  842.95  1607.7  842.34  1729.1  825.63    1820  818.22
#Mann= 3 , 0 , 0
       0     .08       0   907.7    .045       0   932.7     .08       0
Bank Sta=907.7,932.7
XS Rating Curve= 0 ,0
Exp/Cntr=0.3,0.1

Type RM Length L Ch R = 1 ,11380.3 ,354.9,349.1,341
XS GIS Cut Line= 3
     1532909.105      404644.789       1532374.8      403902.974
     1531908.413      403121.528
#Sta/Elev= 30
    10.2  945.87    71.1  961.72    91.4  965.51   111.7  963.51   132.1  958.82
   152.4  952.28   182.8  939.22   253.9  899.75   335.2  869.01   375.8  861.25
   487.6  846.39   568.8   827.5   639.9   805.3   843.1  730.99   873.6  723.42
   883.7  719.37     904  707.01   914.2  704.59   926.7  704.78  1086.1  711.39
  1096.2  714.14  1146.8  737.09  1278.2  791.38  1409.7  836.65  1429.9  841.17
    1531  852.95  1611.9  867.37  1682.7  888.21  1773.7  922.85  1824.2  935.25
#Mann= 3 , 0 , 0
    10.2     .08       0     904    .045       0   926.7     .08       0
Bank Sta=904,926.7
XS Rating Curve= 0 ,0
Exp/Cntr=0.3,0.1

Type RM Length L Ch R = 1 ,11031.1 ,398,400,402.3
XS GIS Cut Line= 3
     1533305.659      404287.144     1532645.542      403686.894
      1531957.53      403073.289
#Sta/Elev= 30
    10.1  869.16   141.9  913.77   152.1  916.88   162.2  916.93   304.2  872.77
     436  843.35   527.2  818.82   577.9   810.1   598.2  808.94   628.6  810.56
   638.7  808.15   689.4  789.02   811.1  735.64   841.5  724.72   882.1   704.9
   889.8  702.88   902.3  701.93   914.8  702.24  1064.4  706.74  1084.7  714.15
  1115.1  729.52  1206.3  782.49  1277.2  816.56  1317.7  832.92    1338  838.13
  1439.3  856.14  1591.2  899.21  1682.4  919.46  1753.3  937.69  1814.1  947.74
#Mann= 3 , 0 , 0
       0     .08       0   889.8    .045       0   914.8     .08       0
Bank Sta=889.8,914.8
XS Rating Curve= 0 ,0
Exp/Cntr=0.3,0.1

Type RM Length L Ch R = 1 ,10631.1 ,401.3,400,397
XS GIS Cut Line= 3
      1533517.04      404034.316     1532886.888      403369.137
     1532261.691      402709.799
#Sta/Elev= 30
    10.1  899.52   110.8   913.7     151  915.66   191.3  920.24   211.4  918.42
   312.1  885.87   352.4  879.71   463.2  857.72     584  822.88   634.3  804.36
   775.3  745.39   845.8  722.35   903.8  700.43   916.3   698.3   928.8  698.35
  1027.3  700.17  1047.5  702.92  1148.5  740.51  1209.1   768.3  1229.2   774.4
  1269.6  773.51  1320.1   767.4  1390.8  764.53  1400.9   765.6    1411  768.56
  1441.3  783.07  1491.7  801.62  1572.5  827.65  1713.8  848.23  1824.9  871.53
#Mann= 3 , 0 , 0
    10.1     .08       0   903.8    .045       0   928.8     .08       0
#XS Ineff= 2 , 0
                          980.47          718.33
Permanent Ineff=
       F       F
Bank Sta=903.8,928.8
XS Rating Curve= 0 ,0
Exp/Cntr=0.3,0.1

Type RM Length L Ch R = 1 ,10231.1 ,321,327.9,336.2
XS GIS Cut Line= 3
     1533817.296       403724.25     1533140.814       403074.41
     1532449.094      402487.321
#Sta/Elev= 30
    10.1  821.65   151.3  870.45   282.4  878.03   342.9  874.54   524.5  840.78
   595.1  815.24   716.1  766.22   736.3  759.83   796.8  748.63   837.2  730.32
   867.4  724.03   877.5  719.36   897.7  706.29   925.5  697.85     938  696.35
   950.5  697.61  1069.1  705.85  1089.3     710  1139.7  736.36  1190.1  749.57
  1240.5  779.41  1331.2  821.47  1351.4  829.31  1381.6  830.58  1411.8  835.68
  1542.9  865.06  1653.8  885.68  1734.4  910.23    1805  945.71  1845.3  958.27
#Mann= 3 , 0 , 0
       0     .08       0   925.5    .045       0   950.5     .08       0
Bank Sta=925.5,950.5
XS Rating Curve= 0 ,0
Exp/Cntr=0.3,0.1

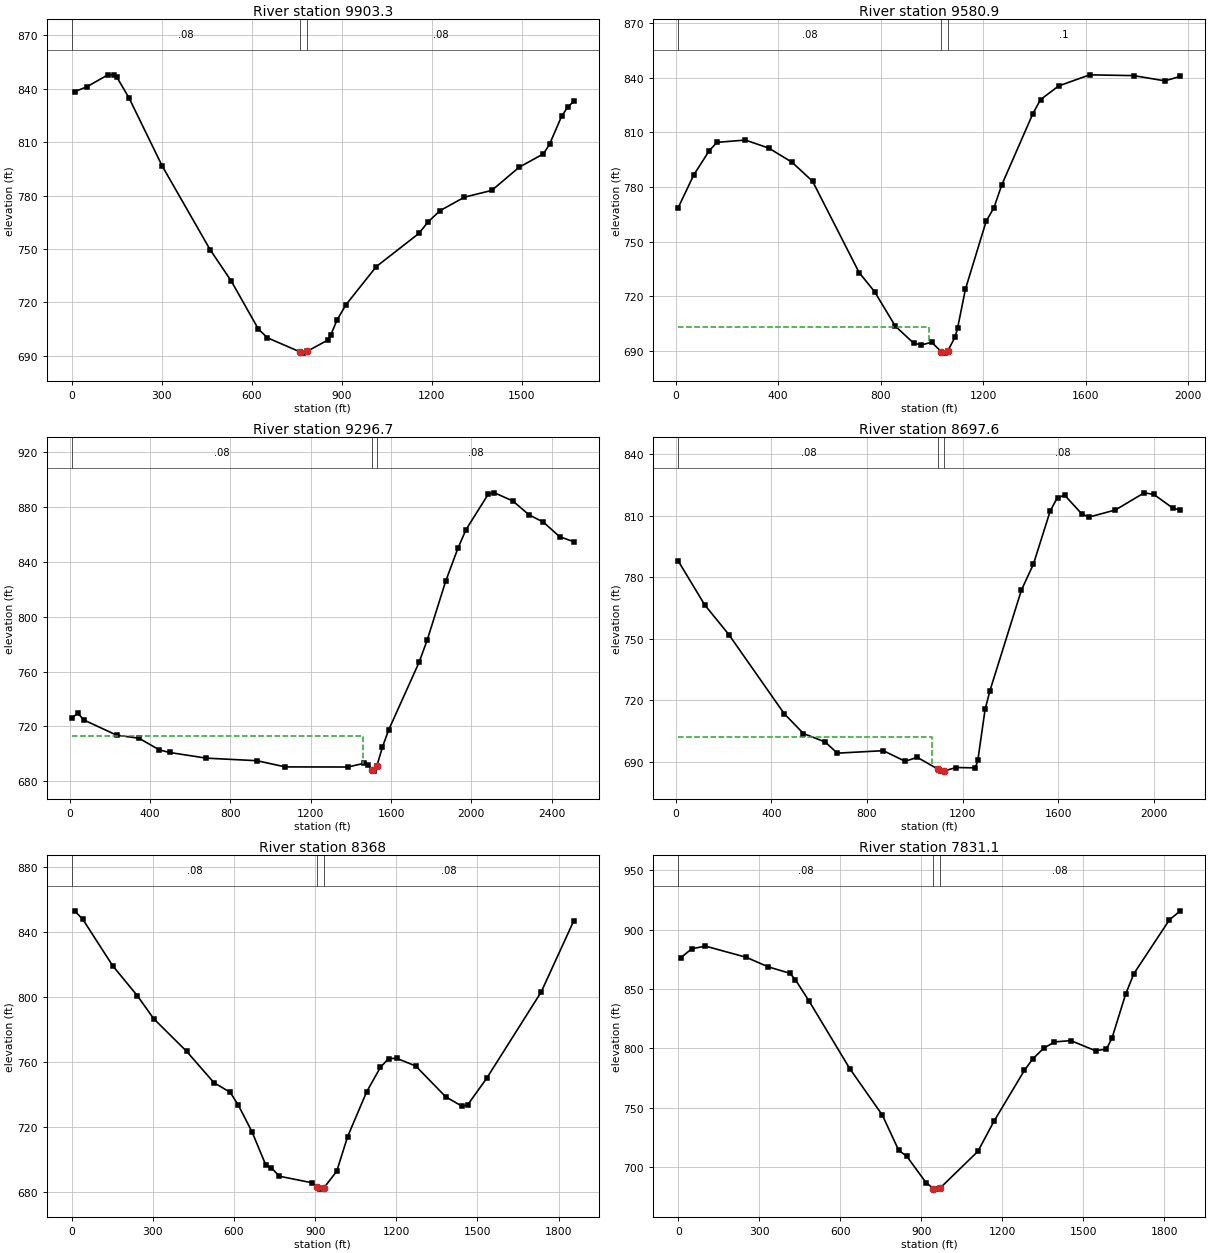
Type RM Length L Ch R = 1 ,9903.3  ,318.9,322.4,326.2
XS GIS Cut Line= 3
     1533782.446      403504.271     1533374.456      402848.314
     1532891.089      402087.116
#Sta/Elev= 30
      10  838.27    50.2  840.99   120.4  847.68   140.5   847.7   150.5  846.31
   190.6  834.85     301  796.73   461.5  749.57   531.7  732.06     622  705.15
   652.1  700.21     760  692.37   772.5  691.59     785  692.61   853.5  698.89
   863.7  701.71   883.9  709.98   914.3  718.74  1015.6  740.15  1157.5  758.73
  1187.9  765.17  1228.4  771.55  1309.5  779.08  1400.6  782.87  1491.8  795.86
  1572.9  803.39  1593.1  808.74  1633.7  824.56  1653.9  829.64  1674.2  832.85
#Mann= 3 , 0 , 0
       0     .08       0     760    .045       0     785     .08       0
Bank Sta=760,785
XS Rating Curve= 0 ,0
Exp/Cntr=0.3,0.1

Type RM Length L Ch R = 1 ,9580.9  ,282.2,284.1,286
XS GIS Cut Line= 4
     1533900.172      403786.812     1533770.674      402980.393
     1533605.858      402621.331     1533070.208      402085.681
#Sta/Elev= 30
    10.1  768.68    70.6  786.57   131.1   799.9   161.3  804.47   272.3  805.73
     363  801.34   453.8  793.59   534.4  783.12   715.9  733.07   776.4  722.54
   857.3  703.66   928.2  694.39   958.6  693.35   999.1  694.81  1037.2  689.58
  1049.7  688.86  1062.2  690.15  1090.3  697.63  1100.4   702.7  1130.8   723.9
  1211.8  761.23  1242.1   768.6  1272.4  781.06  1393.6  820.08  1423.9  827.92
  1494.6   835.4  1615.8  841.51  1787.6  841.07  1908.8  838.21  1969.4  840.64
#Mann= 3 , 0 , 0
    10.1     .08       0  1037.2    .045       0  1062.2      .1       0
#XS Ineff= 2 , 0
          989.49  703.17
Permanent Ineff=
       F       F
Bank Sta=1037.2,1062.2
XS Rating Curve= 0 ,0
Exp/Cntr=0.3,0.1

Type RM Length L Ch R = 1 ,9296.7  ,617.4,599.1,622.2
XS GIS Cut Line= 5
     1534043.593      404109.261     1534116.939       403270.54
     1533968.884      402759.142     1533822.858       402380.17
     1533298.043      401873.547
#Sta/Elev= 30
    10.1  726.34    40.6  729.49      71  724.65   233.3  713.62   344.9  711.37
   446.3  702.83     497  700.98   679.6  696.84   932.3  694.97    1073  690.44
  1384.5  690.36  1465.7  693.08    1486  692.16    1504  688.36  1516.5  687.36
    1529  691.11  1557.1     705  1587.5   717.3  1739.8  766.94  1780.5  783.37
  1871.6  825.93  1932.4  849.97  1972.9  863.63  2084.4  889.71  2114.8  890.54
    2206   884.6    2287  874.45  2357.9  869.18    2439  858.53  2509.9  854.82
#Mann= 3 , 0 , 0
    10.1     .08       0    1504    .045       0    1529     .08       0
#XS Ineff= 2 , 0
         1460.84  713.27
Permanent Ineff=
       F       F
Bank Sta=1504,1529
XS Rating Curve= 0 ,0
Exp/Cntr=0.3,0.1

Type RM Length L Ch R = 1 ,8697.6  ,334.4,329.6,284
XS GIS Cut Line= 4
     1535036.024      403025.848     1534827.141      402512.593
     1534075.162      402070.955     1533430.609        401838.2
#Sta/Elev= 30
    10.1   787.9   120.9  766.53   221.7  752.08   453.4  713.53     534  703.83
   625.1   699.7   675.8  694.26   868.5  695.46   959.7   690.3  1010.5  692.21
  1099.4  686.32  1111.9   685.5  1124.4  685.63  1172.7  687.25  1253.8   687.1
    1264   690.8  1294.4  715.55  1314.7   724.7  1446.4  773.71  1496.8  786.41
  1567.3  812.41  1597.5  818.85  1627.8  819.94  1698.3  810.95  1728.5  809.29
  1839.4  812.75  1960.3  821.13  2000.6  820.36  2081.3  813.59  2111.5  812.71
#Mann= 3 , 0 , 0
    10.1     .08       0  1099.4    .045       0  1124.4     .08       0
#XS Ineff= 2 , 0
          1072.5  702.34
Permanent Ineff=
       F       F
Bank Sta=1099.4,1124.4
XS Rating Curve= 0 ,0
Exp/Cntr=0.3,0.1

Type RM Length L Ch R = 1 ,8368    ,539.8,536.9,530.7
XS GIS Cut Line= 3
     1535200.639      402289.437     1534322.918      401984.103
      1533464.37      401634.378
#Sta/Elev= 30
    10.1  852.98    40.4  847.85   151.5  819.11   242.4  800.74     303  786.54
   424.3  766.53   525.3  747.24   585.9  741.19   616.2  733.24   666.7  716.83
   717.2  696.56   737.4  694.86   767.7  689.58   888.9  685.53   906.7   683.1
   919.2  681.64   931.7  682.27   979.7  692.68    1020     714  1090.5  741.61
  1140.9  756.53  1171.2     762  1201.4  762.17  1271.9  757.43  1382.8  738.46
  1443.2  732.65  1463.4  733.43  1533.9  749.83  1735.4  802.94  1856.4  846.91
#Mann= 3 , 0 , 0
       0     .08       0   906.7    .045       0   931.7     .08       0
Bank Sta=906.7,931.7
XS Rating Curve= 0 ,0
Exp/Cntr=0.3,0.1

Type RM Length L Ch R = 1 ,7831.1  ,387.2,400,413.9
XS GIS Cut Line= 3
      1535388.52      401728.113     1534458.814      401499.486
      1533569.26      401352.388
#Sta/Elev= 30
    10.1  876.42    50.4  883.85   100.8  886.05   251.9  876.65   332.6  868.63
   413.2  863.18   433.4  857.85   483.7  840.04   634.9   782.9   755.8  743.59
   816.3  713.96   846.5  708.87   917.1  686.81   944.9  681.72   957.4  681.25
   969.9  682.22  1109.4  713.06  1170.1  738.87  1281.6  781.27    1312  790.86
  1352.5  799.87    1393  805.31  1453.8  806.43    1545  797.87  1585.5  799.31
  1605.8  808.37  1656.4  845.46  1686.8  862.75  1818.5  908.17    1859  915.81
#Mann= 3 , 0 , 0
       0     .08       0   944.9    .045       0   969.9     .08       0
Bank Sta=944.9,969.9
XS Rating Curve= 0 ,0
Exp/Cntr=0.3,0.1

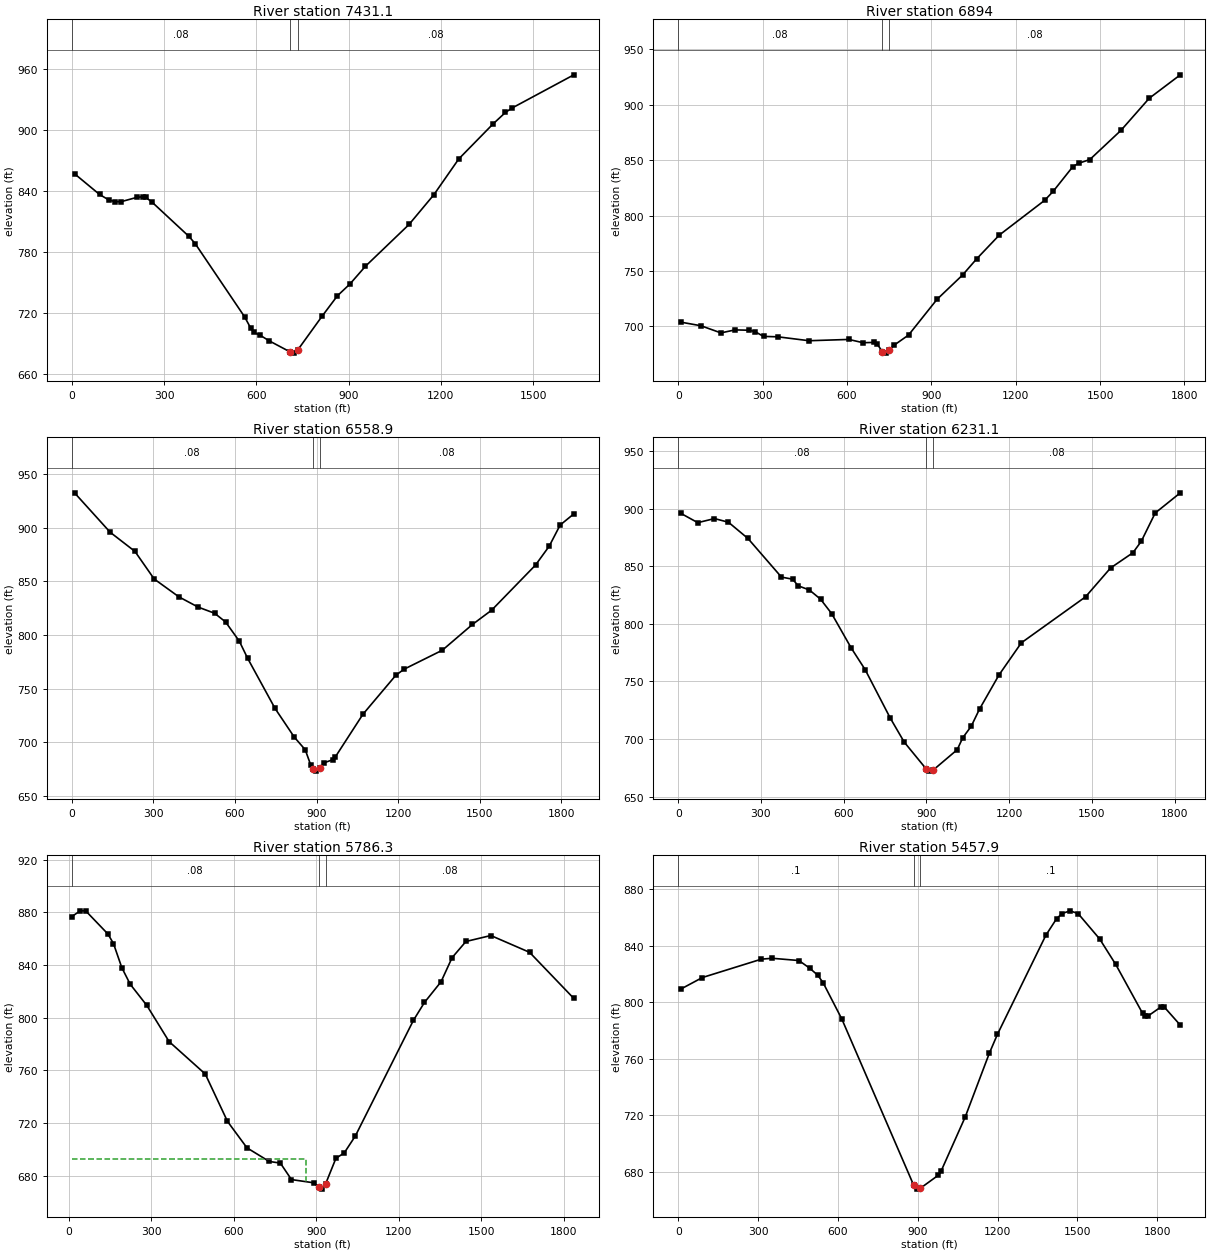
Type RM Length L Ch R = 1 ,7431.1  ,538.7,537.1,536.4
XS GIS Cut Line= 3
     1535163.512        401611.1     1534615.083      401141.121
     1533905.118      400571.841
#Sta/Elev= 30
      10  856.79    90.3  836.66   120.4  831.26   140.4  829.58   160.5  829.55
   210.7  833.72   230.7  834.43   240.8  833.72   260.8  829.15   381.2  795.27
   401.3  788.22   561.8  716.19   581.8  705.05   591.8  700.83   611.9  698.13
     642   692.5   709.8  681.63   722.3  680.42   734.8  683.59   813.3  716.58
   863.8  736.93   904.3  748.45   954.8  765.97  1096.4  807.08  1177.3  836.44
  1258.2  871.65  1369.4  906.03  1409.8  917.38    1430  921.53  1632.3  954.46
#Mann= 3 , 0 , 0
       0     .08       0   709.8    .045       0   734.8     .08       0
Bank Sta=709.8,734.8
XS Rating Curve= 0 ,0
Exp/Cntr=0.3,0.1

Type RM Length L Ch R = 1 ,6894    ,357.3,335.2,313.1
XS GIS Cut Line= 3
     1535553.477       401169.63     1534736.757      400573.646
     1533968.815      400475.968
#Sta/Elev= 30
    10.1  703.88    80.9  700.66   151.7  694.22   202.2  696.94   252.8  696.61
     273  695.38   303.3  691.05   353.9   690.7   465.1  687.16   606.6  688.32
   657.2  685.36   697.6  685.65   707.7  684.02   725.6  677.39   738.1  675.97
   750.6  678.84   768.4   683.3     819   692.3   920.1  724.48  1011.1  746.47
  1061.3  761.09  1141.8  782.53  1302.6  813.77  1332.8  821.81  1403.1  844.24
  1423.3  847.22  1463.5  850.61  1574.1  876.93  1674.6  905.89  1785.2  927.06
#Mann= 3 , 0 , 0
       0     .08       0   725.6    .045       0   750.6     .08       0
Bank Sta=725.6,750.6
XS Rating Curve= 0 ,0
Exp/Cntr=0.3,0.1

Type RM Length L Ch R = 1 ,6558.9  ,329.2,327.7,326.1
XS GIS Cut Line= 3
      1535847.79      400323.479     1534773.547      400441.205
     1534008.332      400419.131
#Sta/Elev= 30
    10.1  932.54   141.4  895.76   232.3  877.98     303  852.27   393.9  835.64
   464.6  826.09   525.2  820.36   565.6  812.23   616.1  794.35   646.4  778.51
   747.4  731.72   818.1     705   858.5  693.18   878.7  678.96   886.4  675.15
   898.9  673.28   911.4  676.19   929.2  681.18   959.5  683.88   969.6  686.68
  1070.6  726.24  1191.5  762.54  1221.7   768.2  1362.7  785.93  1473.5  809.95
    1544  823.23  1705.2  865.22  1755.6  882.83  1795.8  902.53  1846.2  912.93
#Mann= 3 , 0 , 0
       0     .08       0   886.4    .045       0   911.4     .08       0
Bank Sta=886.4,911.4
XS Rating Curve= 0 ,0
Exp/Cntr=0.3,0.1

Type RM Length L Ch R = 1 ,6231.1  ,436.5,444.8,454.5
XS GIS Cut Line= 3
     1535775.467      399959.331     1534876.746      400105.629
      1533979.23       400257.64
#Sta/Elev= 30
    10.1  895.76    70.8  887.77   131.5  891.31   182.1  888.13   252.9  874.03
   374.3  840.53   414.8  838.72     435  832.97   475.5  829.37     516  821.39
   556.4  808.86   627.3  779.02   677.9  760.22   768.9  718.22   819.5  697.38
     898  674.43   910.6  672.18     923  672.79  1011.7  690.76  1031.9  701.18
  1062.3  711.01  1092.6  726.01  1163.4  755.69  1244.3  783.51    1477  823.38
    1568  848.47  1648.9  861.66  1679.2  871.57  1729.8  896.16  1820.8  913.65
#Mann= 3 , 0 , 0
       0     .08       0     898    .045       0     923     .08       0
Bank Sta=898,923
XS Rating Curve= 0 ,0
Exp/Cntr=0.3,0.1

Type RM Length L Ch R = 1 ,5786.3  ,324,328.4,331.7
XS GIS Cut Line= 3
     1535768.805      399797.147     1534846.447      399669.142
     1533960.267       399479.43
#Sta/Elev= 30
    10.1  876.73    40.5  881.11    60.7  881.13   141.7  863.54   161.9   856.3
   192.3  837.98   222.7  825.47   283.4  809.32   364.4  781.92     496  757.33
   576.9  721.36   647.8  701.32   728.8  690.99   769.3  689.75   809.7  677.24
   890.7   674.8   908.6   671.5   921.1     670   933.6  673.77   971.5  693.37
  1001.7  697.45    1042  710.23  1253.4  797.98  1293.7   811.6  1354.1  827.31
  1394.4  845.62  1444.7  857.87  1535.4  862.39  1676.3  849.66  1837.5  814.65
#Mann= 3 , 0 , 0
    10.1     .08       0   908.6    .045       0   933.6     .08       0
#XS Ineff= 2 , 0
          864.16  692.74
Permanent Ineff=
       F       F
Bank Sta=908.6,933.6
XS Rating Curve= 0 ,0
Exp/Cntr=0.3,0.1

Type RM Length L Ch R = 1 ,5457.9  ,393.5,384.1,371.5
XS GIS Cut Line= 3
     1535829.147      399628.106     1534722.042      399286.025
     1533997.568      399353.237
#Sta/Elev= 30
    10.1  809.32    90.7  817.44   312.4  830.44   352.7  831.07   453.4  829.47
   493.7  824.08     524  819.12   544.1  813.84   614.6  788.08   884.3  670.61
   896.8  667.73   909.3   668.3   977.4   677.6   987.5  680.47  1078.1  718.74
  1168.9  763.94  1199.2  777.24  1381.1  847.34  1421.5  859.08  1441.7  862.69
    1472  864.64  1502.3   862.7  1583.2  844.76  1643.8  826.67  1744.9     792
    1755  790.07  1765.1  790.24  1815.6   796.9  1825.7  796.63  1886.3  783.75
#Mann= 3 , 0 , 0
       0      .1       0   884.3    .045       0   909.3      .1       0
Bank Sta=884.3,909.3
XS Rating Curve= 0 ,0
Exp/Cntr=0.3,0.1

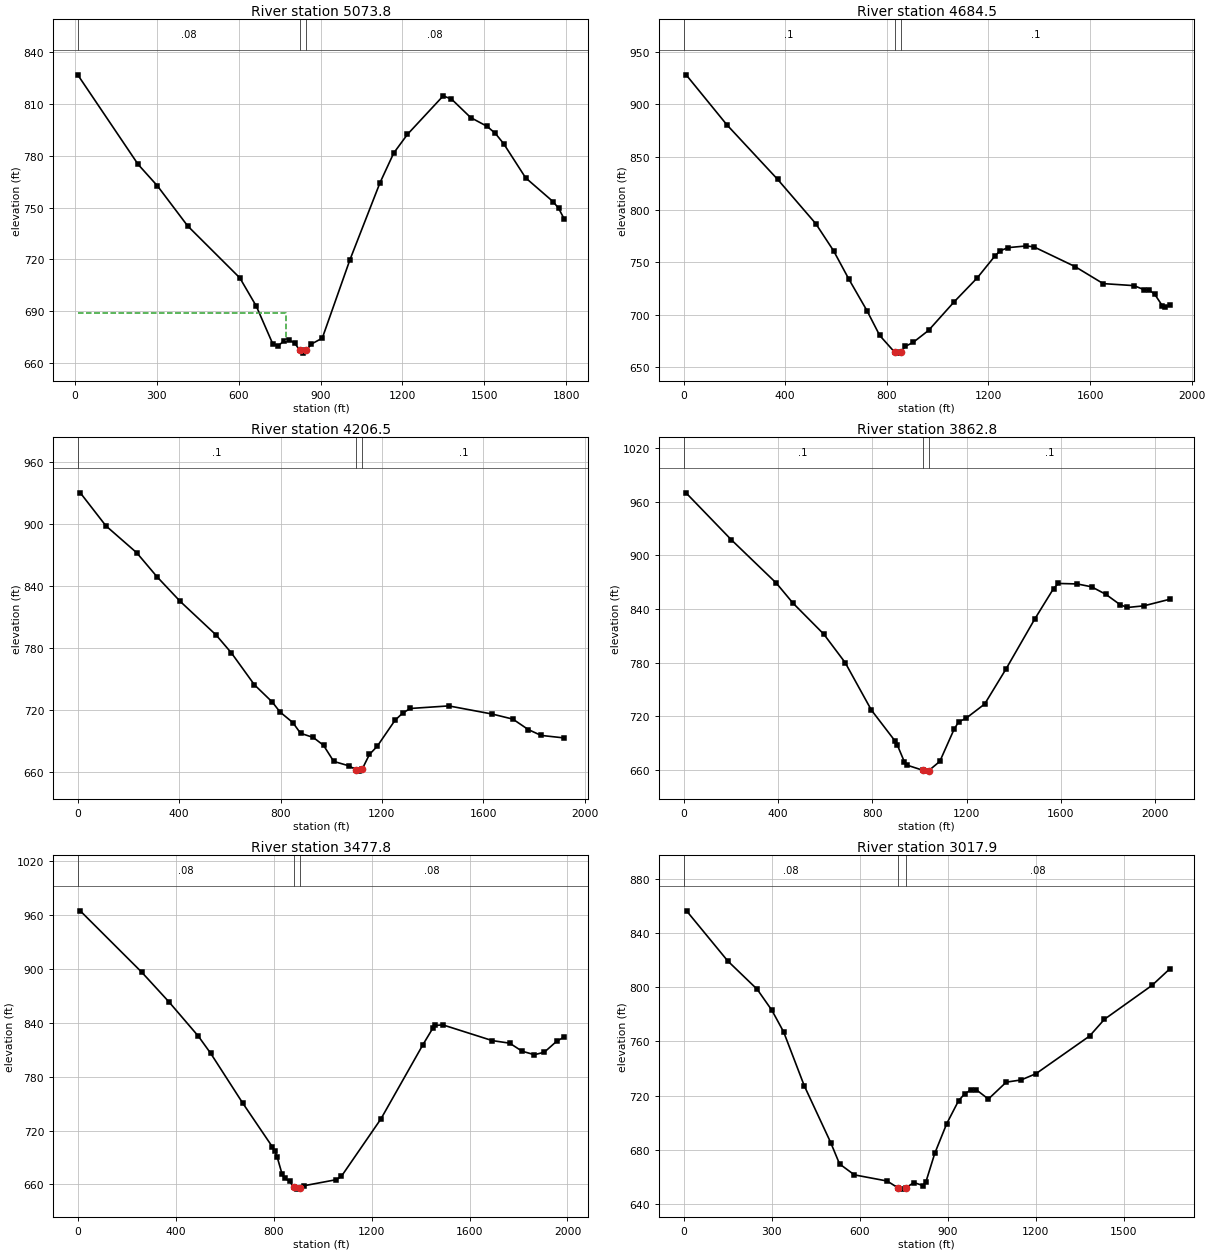
Type RM Length L Ch R = 1 ,5073.8  ,410.2,389.3,371.6
XS GIS Cut Line= 3
     1535855.148      398947.564     1535020.111      398984.239
     1534074.552       399131.51
#Sta/Elev= 30
    10.1  826.97   231.6     775   302.1   762.6   412.9  739.39   604.2  709.24
   664.6  692.85   725.1  670.93   745.2  669.85   765.3   672.7   785.5  673.15
   805.6  671.39   823.3   667.4   835.8  665.63   848.3  667.27   866.1  670.86
   906.4  674.31  1007.1  719.47  1117.9  764.39  1168.3  781.63  1218.6  792.46
  1349.6  814.76  1379.8  812.94  1450.3  802.19  1510.7  797.08    1541  792.96
  1571.2  787.05  1651.8  767.24  1752.5  753.43  1772.7  749.57  1792.8   743.5
#Mann= 3 , 0 , 0
    10.1     .08       0   823.3    .045       0   848.3     .08       0
#XS Ineff= 2 , 0
          774.71  688.65
Permanent Ineff=
       F       F
Bank Sta=823.3,848.3
XS Rating Curve= 0 ,0
Exp/Cntr=0.3,0.1

Type RM Length L Ch R = 1 ,4684.5  ,472.1,478,483.9
XS GIS Cut Line= 4
     1535619.697      398263.286     1535047.443      398475.164
       1534729.4      398800.408     1533952.609      399143.714
#Sta/Elev= 30
      10  928.11   170.1  880.68   370.1  828.77   520.2  786.67   590.2  760.93
   650.7  733.82   721.4  704.11     772  680.36   830.2  664.62   842.7   663.6
   855.2  664.76   873.1  670.06   903.4  673.78     964  685.16  1065.1   712.4
  1156.1   735.2  1226.9  756.38  1247.1  760.98  1277.4  763.87  1348.2  765.45
  1378.5  764.63  1540.3  745.92  1651.5  729.67  1772.8  727.75  1813.3   723.8
  1833.5  723.32  1853.7  719.78  1884.1  708.69  1894.2  707.16  1914.4  709.13
#Mann= 3 , 0 , 0
       0      .1       0   830.2    .045       0   855.2      .1       0
Bank Sta=830.2,855.2
XS Rating Curve= 0 ,0
Exp/Cntr=0.3,0.1

Type RM Length L Ch R = 1 ,4206.5  ,315.3,343.6,372
XS GIS Cut Line= 4
     1535553.477      398116.129     1534736.757      398255.928
     1534332.076       398520.81     1533949.469      398991.711
#Sta/Elev= 30
    10.1  930.24   111.2  898.22   232.4  872.21   313.3  848.71   404.2     825
   545.7  792.45   606.3  775.01   697.2  744.08     768  727.27   798.3  717.69
   848.8  707.45     879  697.11   929.4  693.04   969.7  685.44    1010  669.83
  1070.4   665.5  1098.2  661.66  1110.7   660.4  1123.2  662.79    1151  676.62
  1181.3  684.39  1251.8   709.7    1282  716.68  1312.3  721.15  1463.9  723.64
  1635.9  715.71  1716.8  710.83  1777.4  700.73    1828  695.04    1919  692.59
#Mann= 3 , 0 , 0
       0      .1       0  1098.2    .045       0  1123.2      .1       0
Bank Sta=1098.2,1123.2
XS Rating Curve= 0 ,0
Exp/Cntr=0.3,0.1

Type RM Length L Ch R = 1 ,3862.8  ,416.3,385,353.7
XS GIS Cut Line= 4
     1535542.654      397943.077     1534788.262      398197.065
      1534354.15      397991.046      1533593.92      398188.923
#Sta/Elev= 30
    10.1  969.73   201.5  917.48     393  868.86   463.5  846.55   594.5  811.75
   685.2  779.92     796  727.01   896.1  692.53   906.1  687.94   936.2  668.99
   946.2   665.5  1013.7  659.73  1026.2  658.72  1038.7  659.12  1086.3  669.61
  1146.4  705.27  1166.4  713.89  1196.4  717.57  1276.5  733.71  1367.2  772.97
    1488  828.34  1568.6  862.78  1588.7  868.46  1669.3  867.89  1729.7  864.69
  1790.2   856.3  1850.6  844.76  1880.8  841.58  1951.3  843.43  2062.1  850.85
#Mann= 3 , 0 , 0
       0      .1       0  1013.7    .045       0  1038.7      .1       0
Bank Sta=1013.7,1038.7
XS Rating Curve= 0 ,0
Exp/Cntr=0.3,0.1

Type RM Length L Ch R = 1 ,3477.8  ,434.3,459.9,480.3
XS GIS Cut Line= 4
     1535382.579      397345.984     1534722.394      397642.762
     1534442.297      397873.174     1533569.108      398090.422
#Sta/Elev= 30
    10.1  964.76   261.4  896.39     372  863.48   492.6  825.11   542.9  806.05
   673.6  750.67   794.3  702.09   804.4  697.47   814.5  690.49   834.6  671.41
   844.7  666.98   864.9  663.59   882.6  656.76   895.1  654.77   907.6  656.33
   925.3  658.62  1056.3  665.32  1076.4  668.91  1238.2  732.99    1410  815.81
  1450.5  834.21  1460.6  837.07  1490.9  837.74  1693.1  820.19  1763.9  817.35
  1814.4  808.44    1865  804.47  1905.4  807.29    1956   819.5  1986.3  824.16
#Mann= 3 , 0 , 0
       0     .08       0   882.6    .045       0   907.6     .08       0
Bank Sta=882.6,907.6
XS Rating Curve= 0 ,0
Exp/Cntr=0.3,0.1

Type RM Length L Ch R = 1 ,3017.9  ,380.8,386.8,399.2
XS GIS Cut Line= 4
     1534979.124       397411.69     1534428.111      397434.932
      1534046.74      397491.743     1533525.288      397988.467
#Sta/Elev= 30
      10  856.22   150.4  819.29   250.7  798.41   300.8  782.94   340.9  766.99
   411.1  727.34   501.4  685.37   531.4  669.69   581.9  661.64   693.6   657.1
   731.8   651.9   744.3  651.13   756.8  652.05   784.9  655.99   815.3  653.75
   825.5  656.36   855.9  677.52   896.5  699.34   937.1  716.35   957.4  721.27
   977.7   724.1   997.9  724.27  1038.5   717.5  1099.4  729.97  1150.1  731.59
  1200.8  736.21  1383.4  763.95  1434.1  776.32  1596.4  801.34  1657.3  813.58
#Mann= 3 , 0 , 0
       0     .08       0   731.8    .045       0   756.8     .08       0
Bank Sta=731.8,756.8
XS Rating Curve= 0 ,0
Exp/Cntr=0.3,0.1