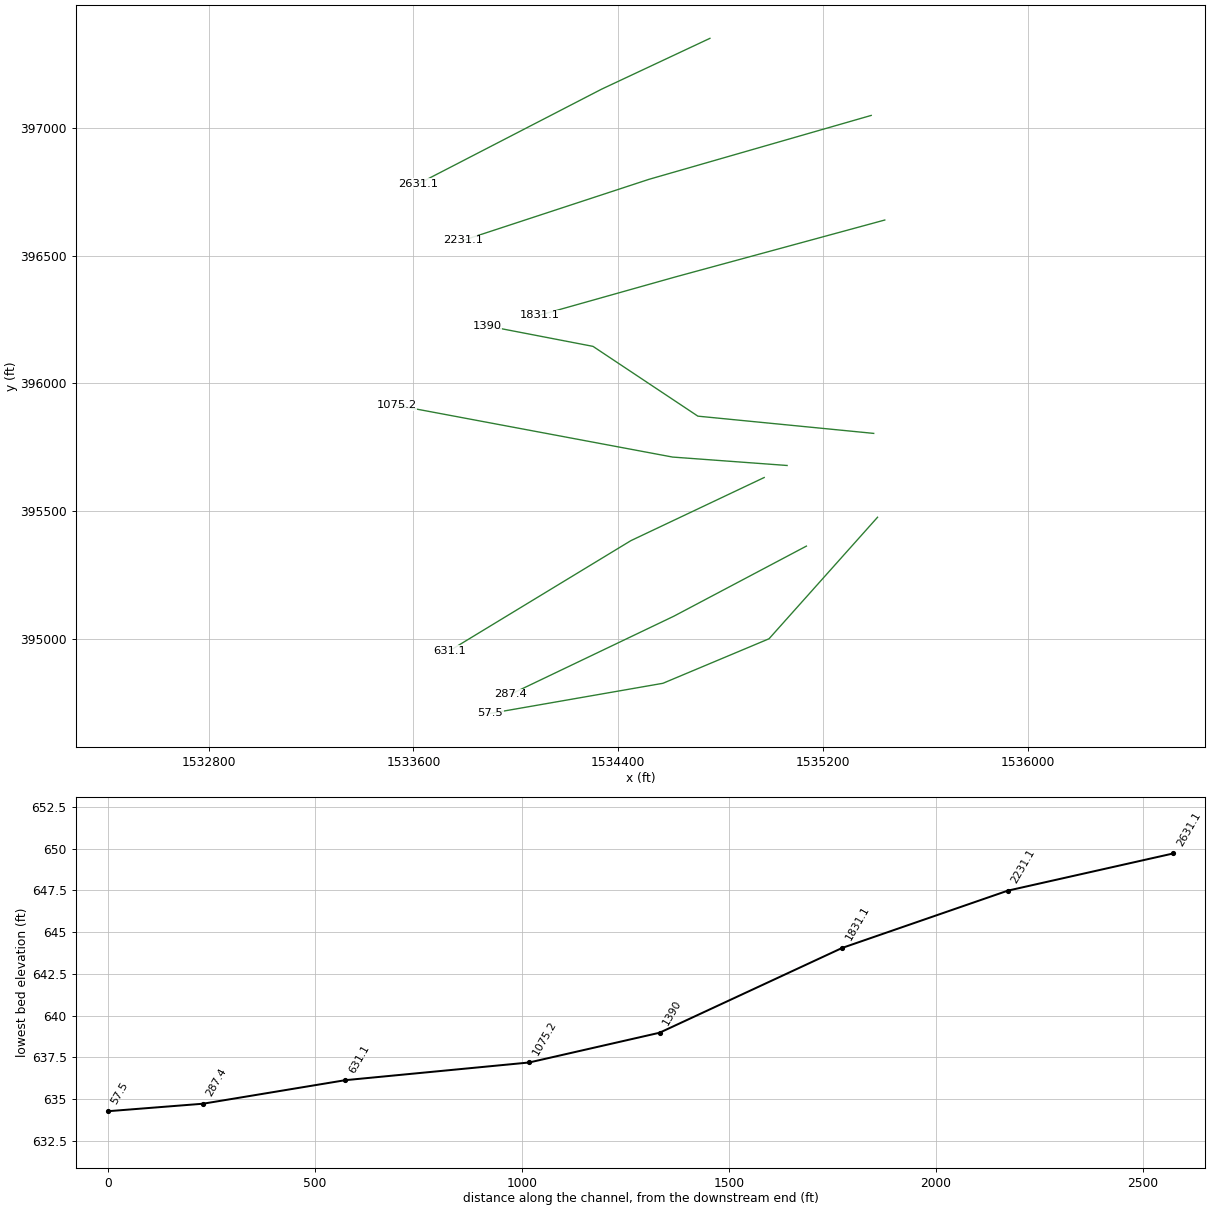
HEC-RAS study LFMILLCR.prj: LFMILLCR

--- LFMILLCR.g01 (geometry) --- (continued)

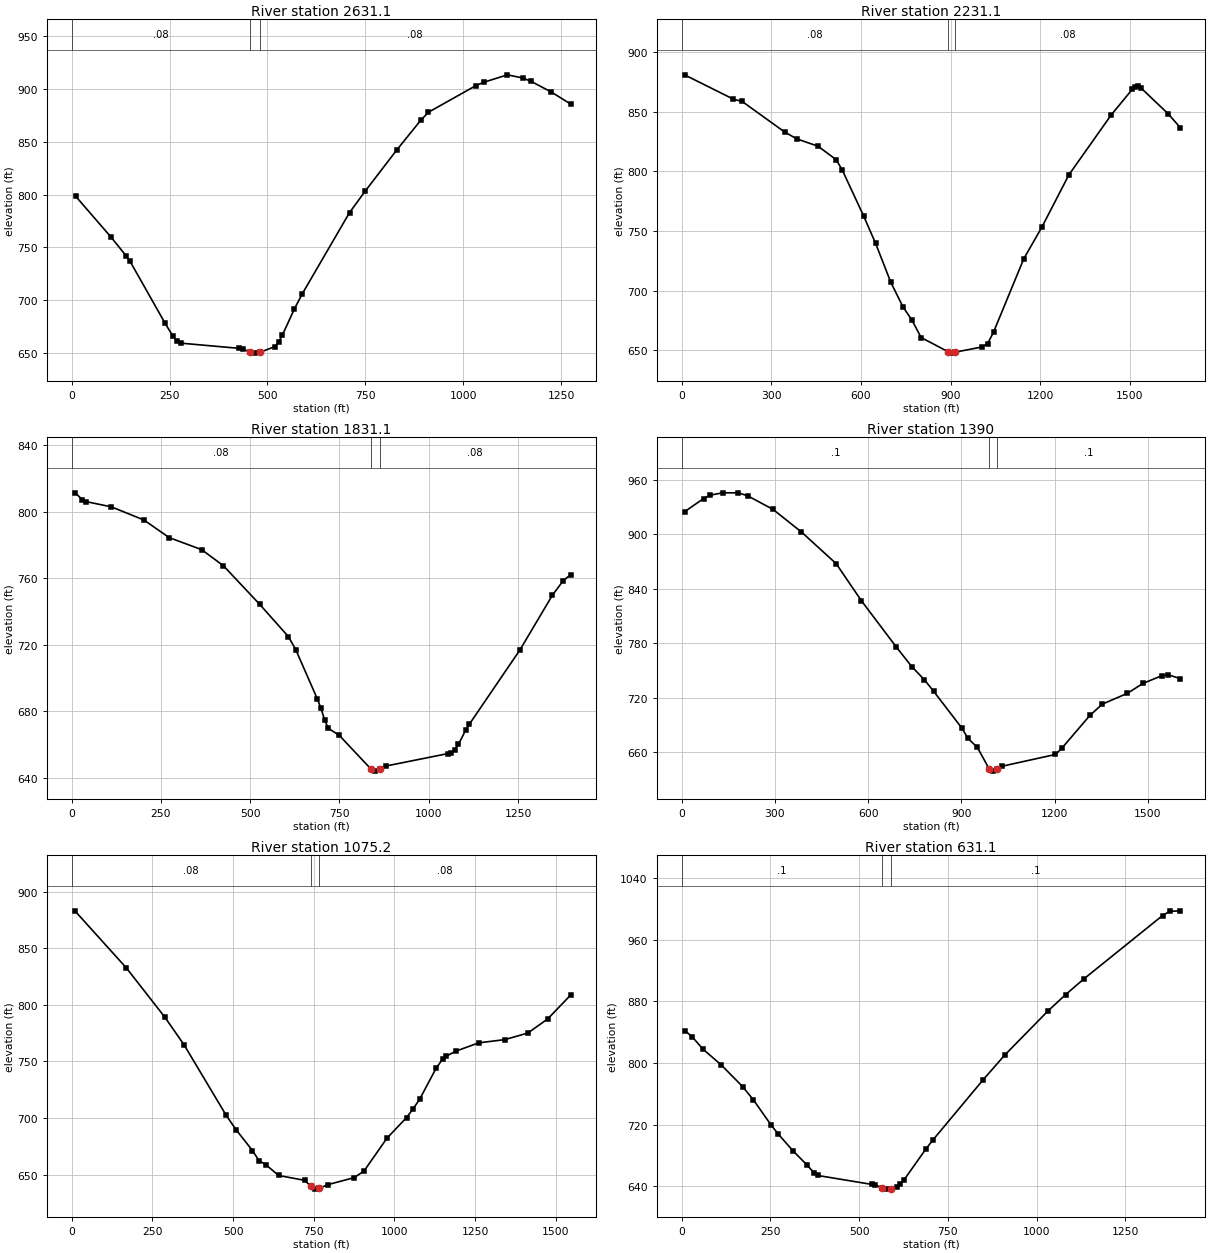
Type RM Length L Ch R = 1 ,2631.1  ,404.2,400,395.7
XS GIS Cut Line= 3
     1534757.801      397350.473     1534334.384       397151.36
     1533618.219      396780.682
#Sta/Elev= 30
      10  798.57    99.6  760.17   139.4   741.9   149.3   736.7   238.9  677.93
   258.8  665.73   268.8   661.1   278.7  659.18   428.1  654.25     438  653.53
   455.4  650.78   467.9  649.72   480.4   650.4   518.3  655.81   528.4  659.96
   538.5  666.98   568.7  691.41   588.9  705.83   709.8  782.94   750.1  803.44
   830.8  842.49   891.3   870.3   911.4   878.1  1032.4   903.3  1052.5  906.48
    1113  913.55  1153.3  910.46  1173.5  907.32  1223.9  897.51  1274.3  885.92
#Mann= 3 , 0 , 0
       0     .08       0   455.4    .045       0   480.4     .08       0
Bank Sta=455.4,480.4
XS Rating Curve= 0 ,0
Exp/Cntr=0.3,0.1

Type RM Length L Ch R = 1 ,2231.1  ,400.4,400,398.8
XS GIS Cut Line= 3
     1535387.629       397048.78     1534520.061      396798.757
     1533792.453      396559.359
#Sta/Elev= 30
    10.1  881.07   172.5  860.75   202.9  858.71   344.9  833.07   385.5  827.32
   456.5  821.16   517.4  809.83   537.7  801.16   608.7  762.85   649.3  739.53
     700  706.94   740.6  686.38     771  675.07   801.4  660.59   890.4  648.84
   902.9  647.49   915.4   648.3  1003.7  652.58  1023.8  655.36    1044  665.32
  1144.8  726.69  1205.2  753.18  1295.9  797.22    1437  847.32  1507.6  868.86
  1517.7  871.26  1527.8   871.6  1537.8  869.79  1628.5   848.2  1668.9   836.5
#Mann= 3 , 0 , 0
       0     .08       0   890.4    .045       0   915.4     .08       0
Bank Sta=890.4,915.4
XS Rating Curve= 0 ,0
Exp/Cntr=0.3,0.1

Type RM Length L Ch R = 1 ,1831.1  ,464.9,441.2,417.2
XS GIS Cut Line= 3
     1535440.608      396639.412     1534620.371      396415.995
      1534093.83        396267.4
#Sta/Elev= 30
    10.1  811.43    30.4  807.23    40.5  806.15   111.3  802.99   202.4   795.1
   273.3  784.49   364.3  777.24   425.1  767.57   526.3  744.46   607.2  724.92
   627.5  717.19   688.2  687.43   698.3  681.87   708.4  674.93   718.6   669.8
   748.9  665.71   837.6  645.46   850.1  644.06   862.6  645.13   880.5  647.14
  1052.8  654.57  1062.9  655.18    1073  656.79  1083.1  660.09  1103.4  668.67
  1113.5  672.18  1255.4  716.94  1346.6  749.95    1377   758.7  1397.2  762.15
#Mann= 3 , 0 , 0
       0     .08       0   837.6    .045       0   862.6     .08       0
Bank Sta=837.6,862.6
XS Rating Curve= 0 ,0
Exp/Cntr=0.3,0.1

Type RM Length L Ch R = 1 ,1390    ,303.4,314.7,326
XS GIS Cut Line= 4
     1535397.397      395804.382     1534710.711      395871.843
     1534301.026      396144.965     1533886.633      396225.019
#Sta/Elev= 30
    10.1  924.85      71  939.35    91.3     943   131.9  945.62   182.6  945.63
   213.1  942.29   294.3  927.35   385.6  902.49   497.2  867.61   578.4  826.76
     690  776.02   740.2  754.23   780.4  739.87   810.6  727.01     901  686.62
   921.1  675.09   951.3  665.11     989  641.64  1001.5  638.98    1014  641.41
  1031.6  644.44  1202.5  657.35  1222.6  664.09    1313  700.28  1353.2  712.82
  1433.6  724.69  1483.8   735.6  1544.1   744.1  1564.2  745.21  1604.4  740.86
#Mann= 3 , 0 , 0
       0      .1       0     989    .045       0    1014      .1       0
Bank Sta=989,1014
XS Rating Curve= 0 ,0
Exp/Cntr=0.3,0.1

Type RM Length L Ch R = 1 ,1075.2  ,426.8,444.1,464.4
XS GIS Cut Line= 3
     1535059.178      395678.773     1534611.821      395711.736
     1533533.457      395914.224
#Sta/Elev= 30
      10     883   169.5  832.62   289.1  788.96   348.9  764.42     479  702.31
   509.5   689.7   560.3  671.25   580.6  662.31     601  658.93   641.6  649.24
   722.9  644.92   740.8  639.59   753.3   637.2   765.8  637.76     794  641.17
   875.3  647.35   905.7  653.11   976.9  682.16  1037.8  700.46  1058.1  708.12
  1078.4  716.68  1129.2  743.92  1149.6  752.13  1159.7  754.42  1190.2  759.04
  1261.3   766.4  1342.6  769.27  1413.7   775.1  1474.7  787.47  1545.8  808.52
#Mann= 3 , 0 , 0
       0     .08       0   740.8    .045       0   765.8     .08       0
Bank Sta=740.8,765.8
XS Rating Curve= 0 ,0
Exp/Cntr=0.3,0.1

Type RM Length L Ch R = 1 ,631.1   ,342.3,343.7,341.1
XS GIS Cut Line= 3
     1534969.706      395631.683     1534449.014      395384.546
     1533740.654      394953.585
#Sta/Elev= 30
    10.1   841.9    30.3  833.88    60.7  817.88   111.2  797.83   171.9  769.44
   202.2  752.34   252.8  719.12     273  707.44   313.5  686.08   353.9  667.33
   374.1  656.91   384.2  653.85   535.9  642.28     546  641.36   563.9   637.8
   576.4  636.14   588.9  636.59   606.7  639.08   616.8  642.64   626.9  648.21
   687.6  687.79   707.8  699.82   849.4  778.08   910.1  810.13  1031.4  867.25
  1081.9  888.82  1132.5  908.94    1355  991.61  1375.2  997.05  1405.5  997.74
#Mann= 3 , 0 , 0
       0      .1       0   563.9    .045       0   588.9      .1       0
Bank Sta=563.9,588.9
XS Rating Curve= 0 ,0
Exp/Cntr=0.3,0.1

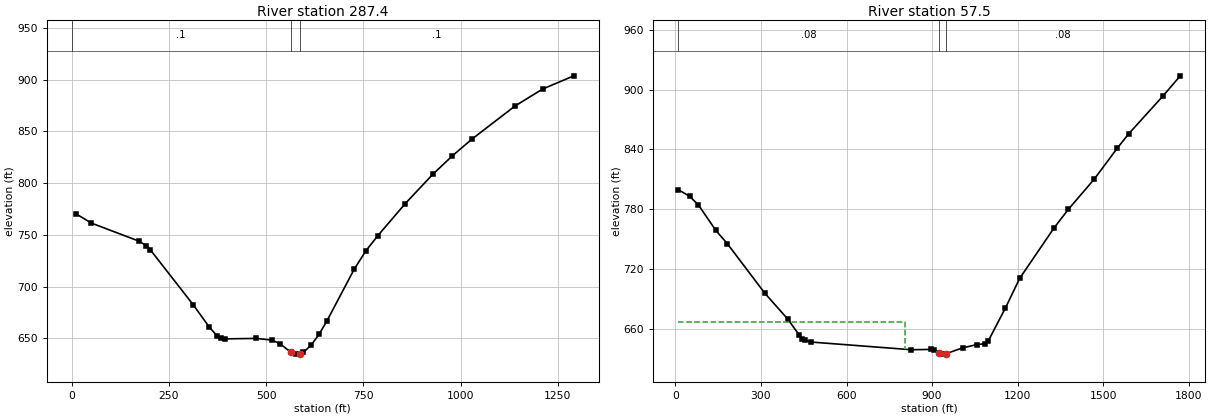
Type RM Length L Ch R = 1 ,287.4   ,232.3,230,228.6
XS GIS Cut Line= 3
     1535134.522      395363.269     1534617.085      395088.992
     1533980.813      394784.061
#Sta/Elev= 30
    10.1  770.48    50.5  761.34   171.7  744.07   191.8  739.58   201.9  735.62
     313  682.09   353.4  660.98   373.6  652.38   383.7  650.01   393.8  649.47
   474.6  649.92     515  648.29   535.1  644.87     563   636.7   575.5  634.73
     588  635.17   595.7   636.5   615.9  643.47     636   653.9   656.2  666.85
   726.7  717.05     757  734.85   787.2  749.25   857.8  780.26   928.3  808.44
   978.7   826.3  1029.1   842.5    1140  874.51  1210.6  890.83  1291.2  903.66
#Mann= 3 , 0 , 0
       0      .1       0     563    .045       0     588      .1       0
Bank Sta=563,588
XS Rating Curve= 0 ,0
Exp/Cntr=0.3,0.1

Type RM Length L Ch R = 1 ,57.5    ,59.6,57.5,55.4
XS GIS Cut Line= 4
     1535412.405      395476.182     1534988.594      395000.572
     1534574.201      394826.339     1533900.812      394708.613
#Sta/Elev= 30
    10.1  799.48    50.6  792.61    80.9  784.07   141.6  758.61     182  745.28
   313.5   695.5   394.4  669.33   434.8  653.22   444.9  649.89     455  648.01
   475.3  646.43   826.8   638.7   896.8     639   906.8  638.41   924.2  635.53
   936.7  634.28   949.2  634.79  1006.7  640.51  1056.6  643.85  1086.6  644.78
  1096.6  647.29  1156.9  680.51  1207.2   710.4  1327.8  761.11  1378.1  779.82
  1468.6  810.05    1549     841  1589.2   855.5  1709.9  893.66  1770.2  913.75
#Mann= 3 , 0 , 0
    10.1     .08       0   924.2    .045       0   949.2     .08       0
#XS Ineff= 2 , 0
          804.16  666.62
Permanent Ineff=
       F       F
Bank Sta=924.2,949.2
XS Rating Curve= 0 ,0
Exp/Cntr=0.3,0.1

Chan Stop Cuts=-1
Use User Specified Reach Order=0